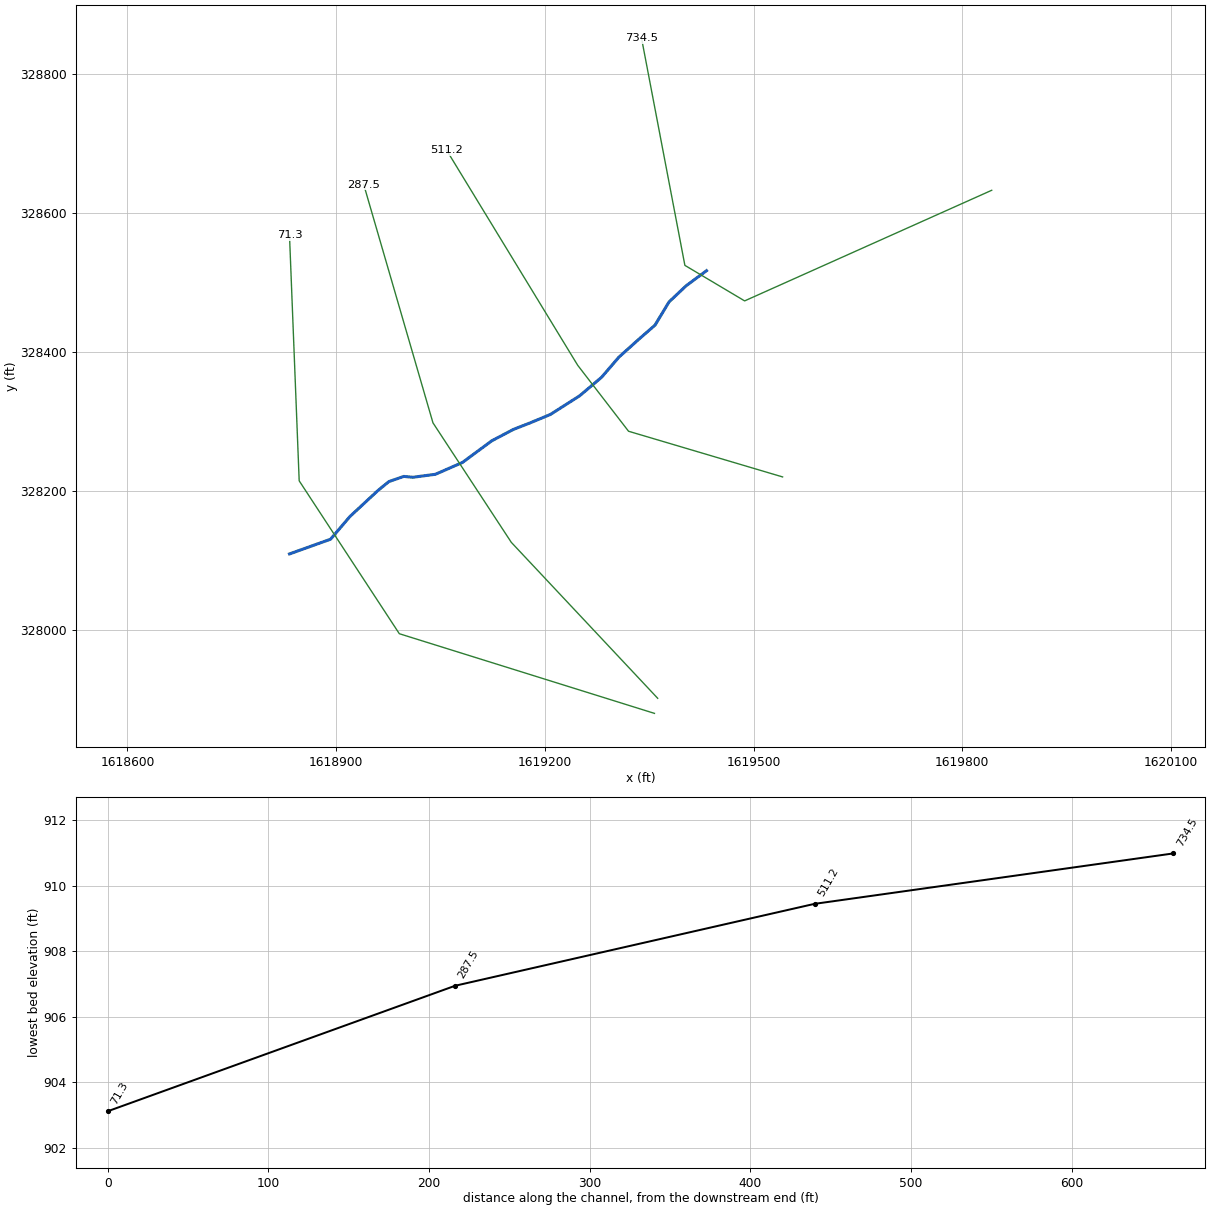
--- hggrrn.prj (project) ---

Proj Title=hggrrn
Current Plan=p01
Default Exp/Contr=0,0
English Units
Geom File=g01
Flow File=f01
Plan File=p01
BEGIN DESCRIPTION:
END DESCRIPTION:
DSS Export Rating Curves= 0
DSS Export Rating Curve Sorted= 0
DSS Export Volume Flow Curves= 0
DXF OffsetX= 0
DXF OffsetY= 0
DXF ScaleX= 0
DXF ScaleY= 0

--- hggrrn.p01 (plan) ---

Plan Title=Floodplain
Program Version=4.00
Geom File=g01
Flow File=f01
K Sum by GR=0
Std Step Tol=0.01
Critical Tol=0.01
Num of Std Step Trials=20
Max Error Tol=0.3
Flow Tol Ratio=0.001
Split Flow NTrial=30
Split Flow Tol=0.02
Split Flow Ratio=0.02
Log Output Level=0
Friction Slope Method=1
Unsteady Friction Slope Method=2
Unsteady Bridges Friction Slope Method=1
Global Log Level=0
CheckData=False
Run HTab=0
Run UNet=0
Run PostProcess=0
UNET Theta=0
UNET Theta Warmup=0
UNET ZTol=0
UNET ZSATol=0
UNET MxIter=0
UNET MaxInSteps=0
UNET DtIC=0
UNET DtMin=0
UNET MaxCRTS=0
UNET WFStab=0
UNET SFStab=0
UNET WFX=0
UNET SFX=0
UNET DSS MLevel=0
UNET DZMax Abort=0
UNET Convert EG Bridges=0
UNET Use Existing IB Tables=0
UNET Froude Limit=0
UNET Froude Power=0
Write IC File=0
Echo Input=False
Echo Output=False
Write Detailed=0

--- hggrrn.f01 (steady flow) ---

Flow Title=NFF Regression Equation
Program Version=4.00
Number of Profiles=1
Profile Names=P100yr
River Rch & RM=hggrrn,Main      ,734.5
     420
River Rch & RM=hggrrn,Main      ,287.5
     422
Boundary for River Rch & Prof#=hggrrn,Main      ,1
Up Type=0
Dn Type=3
Dn Slope=0.011932

--- hggrrn.g01 (geometry) ---

Geom Title=USGS 10m DEM
Program Version=4.00

River Reach=hggrrn          ,Main
Reach XY= 22
     1619432.456        328517.2     1619403.178      328495.517
     1619378.536      328472.299     1619358.336      328438.815
     1619335.809      328419.227     1619306.549      328392.966
     1619281.574      328363.951     1619250.006      328337.288
      1619207.92      328310.455     1619178.368      328298.208
     1619154.862      328289.026     1619123.747      328272.647
      1619081.66      328241.544     1619042.623       328224.47
     1619019.446      328221.422     1619010.297      328220.203
     1618997.298      328221.446     1618975.995        328214.1
     1618960.569      328201.612     1618919.801      328163.782
     1618891.965      328131.164     1618832.933      328110.011

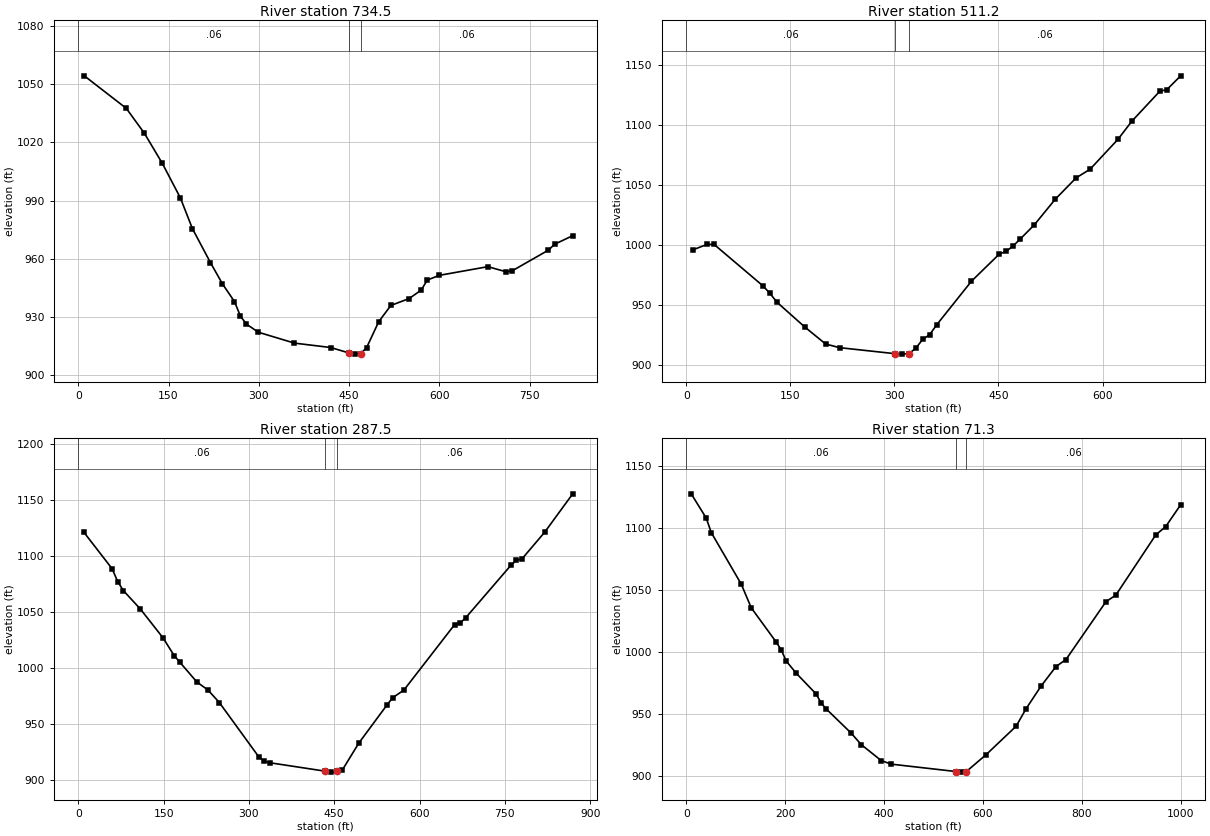
Type RM Length L Ch R = 1 ,734.5   ,233.4,223.4,213.7
XS GIS Cut Line= 4
     1619842.455      328632.799     1619487.252      328473.771
     1619401.353      328524.846     1619339.057      328851.222
#Sta/Elev= 30
      10 1054.18    79.8 1037.44   109.8 1024.65   139.7  1009.1   169.6   991.4
   189.6  975.58   219.5  958.13   239.5  947.14   259.5  938.04   269.4  930.54
   279.4   926.4   299.4  922.23   359.2  916.65   419.2   914.4   449.1  911.65
   459.1  910.99   469.1  911.23   479.1  914.39   499.2  927.73   519.3  936.03
   549.5  939.57   569.7  943.92   579.7  949.09   599.9  951.53   680.4  955.99
   710.6  953.37   720.7  953.82   781.1  964.51   791.2   967.5   821.4  971.95
#Mann= 3 , 0 , 0
       0     .06       0   449.1    .045       0   469.1     .06       0
Bank Sta=449.1,469.1
XS Rating Curve= 0 ,0
Exp/Cntr=0.3,0.1

Type RM Length L Ch R = 1 ,511.2   ,225.6,223.7,221.8
XS GIS Cut Line= 4
     1619541.809      328220.718     1619320.356       328286.38
     1619247.226      328381.275      1619058.92      328690.259
#Sta/Elev= 30
      10  996.41    30.1 1000.88    40.2 1000.82   110.5  966.34   120.5  960.18
   130.6  952.77   170.7  932.12   200.9  917.88   220.9  914.84   300.9  909.82
   310.9  909.45   320.9   909.9   330.8  914.31   340.8  921.77   350.8  925.63
   360.8  933.77   411.1  970.22   451.3  992.86   461.4  995.13   471.4  999.72
   481.5 1005.44   501.6  1017.1   531.7  1038.4   561.9 1056.28     582 1063.45
   622.2 1088.38   642.3 1103.53   682.5 1128.42   692.5  1129.7   712.6 1141.27
#Mann= 3 , 0 , 0
       0     .06       0   300.9    .045       0   320.9     .06       0
Bank Sta=300.9,320.9
XS Rating Curve= 0 ,0
Exp/Cntr=0.3,0.1

Type RM Length L Ch R = 1 ,287.5   ,216.2,216.2,216.1
XS GIS Cut Line= 4
     1619362.273      327902.467     1619151.783      328126.694
     1619039.186      328298.491     1618939.745      328640.731
#Sta/Elev= 30
     9.9  1121.1    59.5 1088.55    69.4    1077    79.4 1068.96   109.1 1052.61
   148.8 1026.97   168.7 1010.94   178.6 1005.05   208.3  987.54   228.2  980.16
     248  969.09   317.3  920.64   327.1  916.67   336.9  915.31   434.5  907.77
   444.5  906.95   454.5  907.66     464  908.65   493.4     933   542.7  966.85
   552.6  973.36   572.4  980.13   661.5 1038.55   671.4 1040.07   681.3 1044.84
   760.4 1091.48   770.3 1096.09   780.2  1097.4   819.8 1121.03   869.3 1155.41
#Mann= 3 , 0 , 0
       0     .06       0   434.5    .045       0   454.5     .06       0
Bank Sta=434.5,454.5
XS Rating Curve= 0 ,0
Exp/Cntr=0.3,0.1

Type RM Length L Ch R = 1 ,71.3    ,77.3,71.3,65.3
XS GIS Cut Line= 4
      1619357.63      327880.799      1618990.82       327995.33
     1618846.881      328215.107     1618832.952      328567.988
#Sta/Elev= 30
    10.1 1127.21    40.5 1107.64    50.6 1096.03   111.2 1054.55   131.5 1035.44
     182 1007.82   192.1 1001.53   202.3  992.51   222.5  982.75   262.9  965.96
     273  958.66   283.2  953.99   333.7   934.5   353.9  925.31   394.4  912.42
   414.6  909.55   546.1  903.58   556.1  903.12   566.1  903.45   606.6  917.21
   667.2  940.08   687.4  954.18   717.6  972.37   747.9  988.14   768.1  993.79
   848.8 1040.28     869  1045.7   949.7 1094.15   969.9 1100.89  1000.1 1118.43
#Mann= 3 , 0 , 0
       0     .06       0   546.1    .045       0   566.1     .06       0
Bank Sta=546.1,566.1
XS Rating Curve= 0 ,0
Exp/Cntr=0.3,0.1

Chan Stop Cuts=-1
Use User Specified Reach Order=0